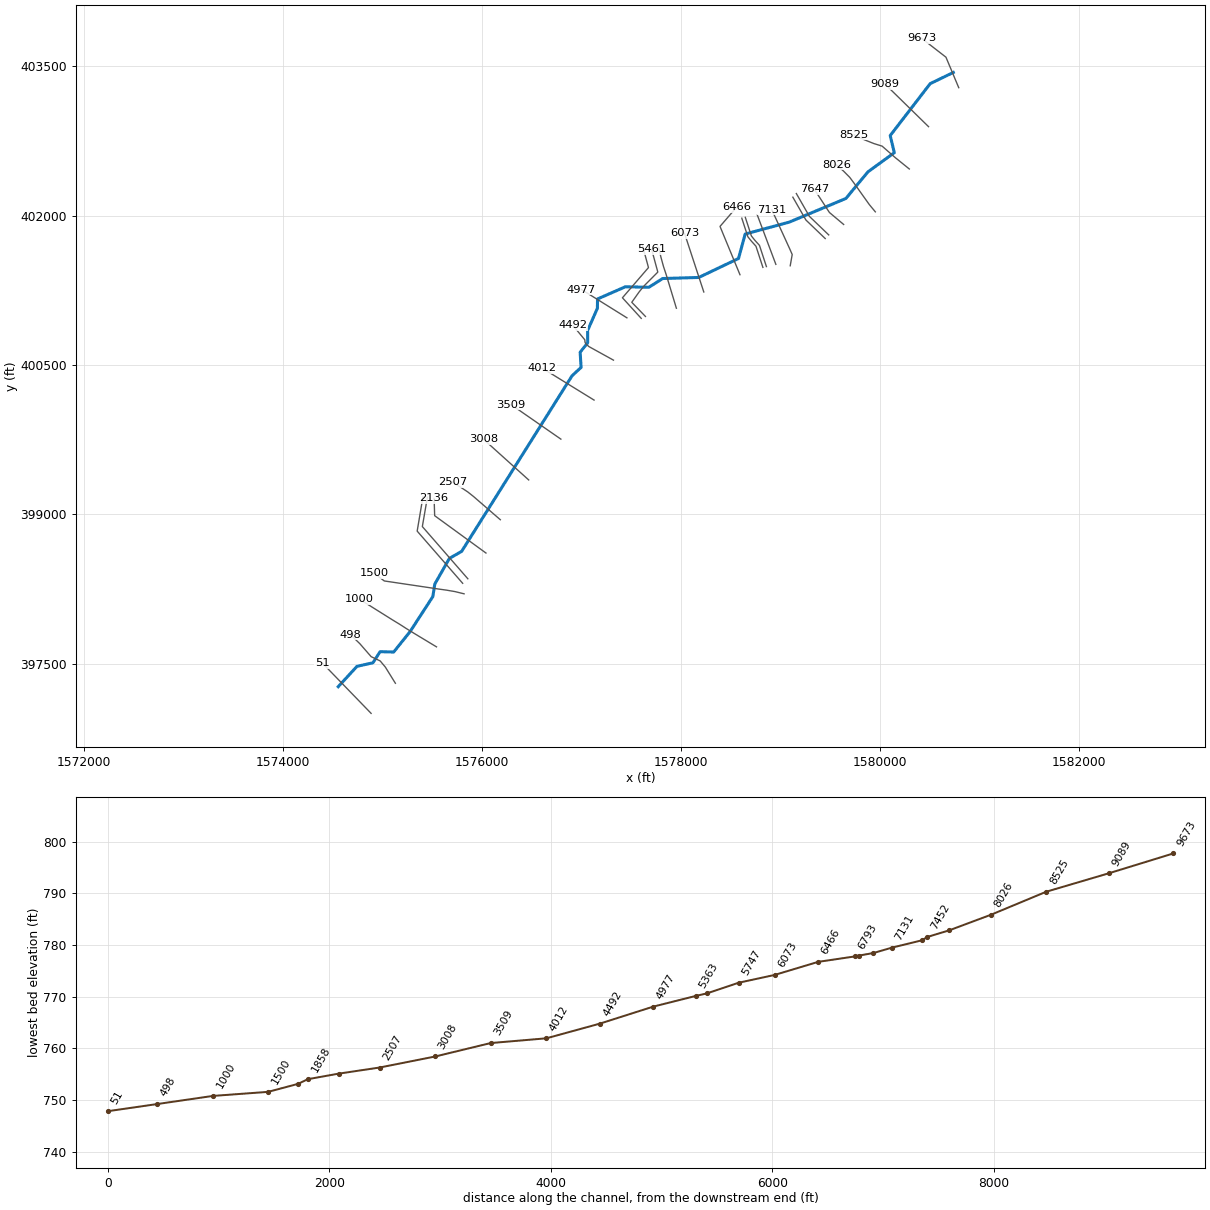
--- PNTPLSNTCK.prj (project) ---

Proj Title=PNTPLSNTCK
Current Plan=p01
Default Exp/Contr=0,0
English Units
Geom File=g01
Flow File=f01
Plan File=p01
BEGIN DESCRIPTION:
---------- MODELED AS PART OF WVEMD CTP PROGRAM, 2023----------
Stream Name: Point Pleasant Creek
Flood Zone:  AFH
Wetzel County, WV
HEC-RAS Version: RAS 6.3
Vertical Datum: NAVD88
Projection: NAD 1983 StatePlane West Virginia S FIPS 4702 (US Feet)
Terrain: 1-meter West Virginia FEMA R3 South Central (collected 2018-2020)
Land Use: 2019 NLCD
Hydrologic Method:
WV 2010 Regional Regression Equations
Additional Model Notes:
None
END DESCRIPTION:
DSS Export Rating Curves= 0
DSS Export Rating Curve Sorted= 0
DSS Export Volume Flow Curves= 0
DXF OffsetX= 0
DXF OffsetY= 0
DXF ScaleX= 0
DXF ScaleY= 0

--- PNTPLSNTCK.p01 (plan) ---

Plan Title=Floodplain
Program Version=6.30
Short Identifier=Floodplain
Geom File=g01
Flow File=f01
Subcritical Flow
K Sum by GR= 0
Std Step Tol= 0.01
Critical Tol= 0.01
Num of Std Step Trials= 20
Max Error Tol= 0.3
Flow Tol Ratio= 0.001
Split Flow NTrial= 30
Split Flow Tol= 0.02
Split Flow Ratio= 0.02
Log Output Level= 0
Friction Slope Method= 1
Unsteady Friction Slope Method= 2
Unsteady Bridges Friction Slope Method= 1
Parabolic Critical Depth
Global Vel Dist= 0 , 0 , 0
Global Log Level= 0
CheckData=True
Encroach Param=-1 ,0,0, 0
Mapping Interval=1HOUR
Computation Time Step Use Courant=        0
Computation Time Step Use Time Series=    0
Computation Time Step Count To Double=0
Computation Time Step Max Doubling=0
Computation Time Step Max Halving=0
Computation Time Step Residence Courant=0
Run HTab= 0
Run UNet= 0
Run Sediment= 0
Run PostProcess= 0
Run WQNet= 0
Run RASMapper= 0
UNET Theta= 0
UNET Theta Warmup= 0
UNET ZTol= 0
UNET ZSATol= 0
UNET MxIter= 0
UNET Max Iter WO Improvement= 0
UNET MaxInSteps= 0
UNET DtIC= 0
UNET DtMin= 0
UNET MaxCRTS= 0
UNET WFStab= 0
UNET SFStab= 0
UNET WFX= 1
UNET SFX= 1
UNET Gravity=32.17405
UNET 1D Methodology=Finite Difference
UNET DSS MLevel= 1
UNET Pardiso=0
UNET DZMax Abort= 0
UNET Use Existing IB Tables= 0
UNET Froude Reduction=False
UNET Froude Limit= 0
UNET Froude Power= 0
UNET D1 Cores= 0
UNET WindReference=Eulerian
UNET WindDragFormulation=Hsu (1988)
UNET D2 Coriolis=0
UNET D2 Cores= 0
UNET D2 Theta= 1
UNET D2 Theta Warmup= 1
UNET D2 Z Tol= 0.01
UNET D2 Volume Tol= 0.01
UNET D2 Max Iterations= 20
UNET D2 Equation= 0
UNET D2 RampUpFraction=0.1
UNET D2 TimeSlices= 1
UNET D2 Turbulence Formulation=Non-Conservative (original)
UNET D2 Eddy Viscosity=0.3
UNET D2 Transverse Eddy Viscosity=0.1
UNET D2 Smagorinsky Mixing=0
UNET D2 BCVolumeCheck=0
UNET D2 Cores=0
UNET D2 SolverType=PARDISO (Direct)
UNET D2 Minimum Iterations= 3
UNET D2 Maximum Iterations= 30
UNET D2 Restart Number= 10
UNET D2 Relaxation Coeff=1.3
UNET D2 SOR Precondition Iterations= 10
UNET D2 ILUT Maximum Fill= 8
UNET D2 ILUT Tolerance=1E-08
UNET D2 Convergence Tolerance=0.00001
UNET D1D2 MaxIter= 0
UNET D1D2 ZTol=0.01
UNET D1D2 QTol=0.1
UNET D1D2 MinQTol=1
Write IC File= 0
Write IC File at Fixed DateTime=0
Write IC File at Sim End=0
Echo Input=False
Echo Parameters=False
Echo Output=False
Write Detailed= 0
HDF Write Warmup=0
HDF Write Time Slices=0
HDF Flush=0
HDF Compression= 1
HDF Chunk Size= 1
HDF Spatial Parts= 1
HDF Use Max Rows=0
HDF Fixed Rows= 1
Calibration Method= 0
Calibration Iterations= 20
Calibration Max Change=0.05
Calibration Tolerance=0.2
Calibration Maximum=1.5
Calibration Minimum=0.5
Calibration Optimization Method= 1
WQ AD Non Conservative
WQ ULTIMATE=-1
WQ Max Comp Step=1HOUR
WQ Output Interval=15MIN
WQ Output Selected Increments= 0
WQ Output face flow=0
WQ Output face velocity=0
WQ Output face area=0
WQ Output face dispersion=0
WQ Output cell volume=0
WQ Output cell surface area=0
WQ Output cell continuity=0
WQ Output cumulative cell continuity=0
WQ Output face conc=0
WQ Output face dconc_dx=0
WQ Output face courant=0
WQ Output face peclet=0
WQ Output face adv mass=0
WQ Output face disp mass=0
WQ Output cell mass=0
WQ Output cell source sink temp=0
WQ Output nsm pathways=0
WQ Output nsm derived pathways=0
WQ Create Restart=0
WQ Fixed Restart=0
WQ System Summary=0
WQ Write To DSS=0
Sorting and Armoring Iterations= 10
XS Update Threshold= 0.02
Bed Roughness Predictor= 0
Hydraulics Update Threshold= 0.02
Energy Slope Method= 1
Volume Change Method= 1
Sediment Retention Method= 0
Sediment TS Multiplier= 1
Warm Up Method= 0
XS Weighting Method= 0
Number of US Weighted Cross Sections= 1
Number of DS Weighted Cross Sections= 1
Upstream XS Weight=0
Main XS Weight=1
Downstream XS Weight=0
Number of DS XS's Weighted with US Boundary= 1
Upstream Boundary Weight= 1
Weight of XSs Associated with US Boundary= 0
Number of US XS's Weighted with DS Boundary= 1
Downstream Boundary Weight= 0.5
Weight of XSs Associated with DS Boundary= 0.5
Percentile Method= 0
Sediment Output Level= 3
Mass or Volume Output= 0
Output Increment Type= 1
Profile and TS Output Increment= 1
Transport Output Increment 1
XS Output Flag= 0
XS Output Increment= 10
Read HDF5 Sediment Hotstart= 0
Sediment Hotstart Type= 0
Write Gradation File= 0
Read Gradation Hotstart= 0
Write HDF5 File= 1
Write Binary Output= 1
Write DSS Sediment File= 0
DSS Sediment Output Type= 1
SV Curve= 0
Specific Gage Flag= 0
Subcell Erosion Methods= 0
Subcell Deposition Methods= 0
Advection Scheme= 1
Matrix Solver= 0
Implicit Weighting Factor= 1
Maximum Outer Loop Convergence Iterations= 5
Convergence Maximum Absolute= 0.001
Convergence RMSE= 0.0001
Grain Fractions Max Abs Error= 0.001
Max Subgrid Regions= 1
Max Subgrid Length Scale= 3.402823E+38
Initial Layer Thickness= 3.402823E+38
Min Layer Thickness= 3.402823E+38
Max Layer Thickness= 3.402823E+38
Number of Layers= 5

--- PNTPLSNTCK.f01 (steady flow) ---

Flow Title=Flow
Program Version=6.31
Number of Profiles= 1
Profile Names=F01pct
River Rch & RM=PNTPLSNTCK,Main,9673
    1110
River Rch & RM=PNTPLSNTCK,Main,7647
    1340
River Rch & RM=PNTPLSNTCK,Main,4977
    1510
River Rch & RM=PNTPLSNTCK,Main,1858
    2050
Boundary for River Rch & Prof#=PNTPLSNTCK,Main            , 1
Up Type= 0
Dn Type= 3
Dn Slope=0.00308
DSS Import GetInterval= 0
DSS Import GetPeak= 0
DSS Import FillOption= 0

--- PNTPLSNTCK.g01 (geometry) ---

Geom Title=Geometry
Program Version=6.30

River Reach=PNTPLSNTCK      ,Main
Reach XY= 30
     1580737.202      403440.014     1580504.585      403327.334
 1580103.3237199402806.145582077     1580144.391      402633.685
     1579880.454      402442.321     1579657.768      402173.799
      1579088.64      401936.217     1578646.324      401816.662
     1578579.098      401571.058     1578179.945      401380.457
      1577817.46      401369.763     1577678.425      401281.911
     1577442.752      401286.8761577162.62374474401164.131935175
1577161.57967071401071.209346624     1577063.079      400847.616
     1577063.842      400723.859     1576988.213      400629.514
     1576997.381      400476.346     1576906.473      400392.314
     1575797.628       398628.781575673.96297944398557.346514088
     1575527.197      398298.763     1575508.099      398174.242
     1575280.829      397824.362     1575114.674      397616.955
     1574978.313      397620.775     1574906.121      397508.859
     1574746.078      397473.336     1574557.387      397268.985

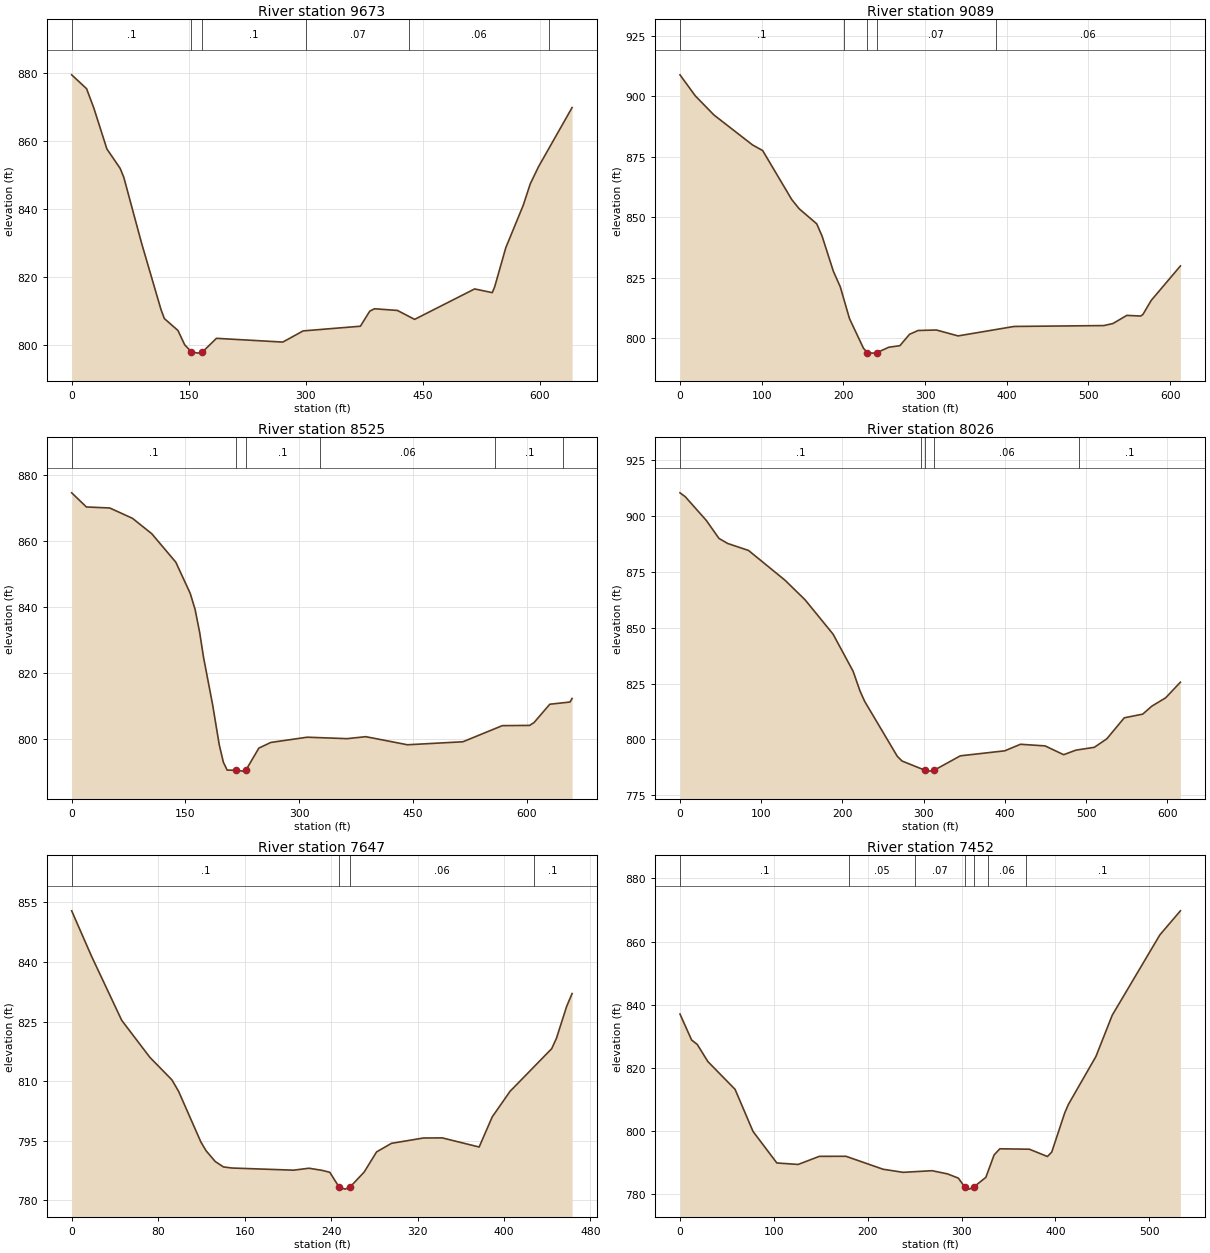
Type RM Length L Ch R = 1 ,9673    ,580.2,583.9,585.7
XS GIS Cut Line= 3
1580791.79414884403286.959460952 1580663.3414619403593.472651258
1580419.30171765403782.876631873
#Sta/Elev= 30
       0   879.5    19.1  875.42    28.5  869.66    45.1  857.72    62.1  852.01
    66.8  849.37    89.6  830.01   114.5  810.47   118.8  807.85   136.2  804.36
   144.8  800.16   153.5  798.04   162.2   797.7  167.61798.0378   185.5  802.05
   270.6  800.95   296.6  804.23     370  805.61     382  810.04   388.1  810.74
   417.4  810.25   439.5  807.62   516.4  816.57     539  815.48   542.1  817.19
   556.3  828.66   578.7  841.16   587.7  847.46   598.3   852.5   641.3  869.88
#Mann= 6 ,-1,0
       0      .1       0   153.5    .045       0  167.61      .1       0
     300     .07       0  432.34     .06       0  612.34      .1       0
Bank Sta=153.5,167.61
XS Rating Curve= 0 ,0
Exp/Cntr(USF)=0,0
Exp/Cntr=0.3,0.1

Type RM Length L Ch R = 1 ,9089    ,563.5,563.9,564.5
XS GIS Cut Line= 6
1580488.46748633402895.4569178541580421.45187233402961.015841844
1580305.28970308 403074.649472851580180.19251233403197.024884271
1580117.64375291403258.2120978561580050.62813892403323.771021845
#Sta/Elev= 30
       0  908.79    18.7  900.12    41.6   892.2    88.7  879.86   101.2  877.51
   136.8  857.28     146  853.44   167.4  847.25     174  842.11   187.7  827.69
   196.2  821.23   207.5  808.08   224.6  795.85  229.47794.0441   235.8  793.85
   241.1  794.04   255.6  796.29   269.1  796.92     281  801.63   291.5   803.2
   313.9   803.4   340.4  800.96     409  804.87   518.8  805.23     530  806.08
   546.9  809.44   563.9  809.17   566.7  809.86   576.8  815.63   612.5  829.85
#Mann= 5 ,-1,0
       0      .1       0  201.25     .07       0  229.47    .045       0
   241.1     .07       0  386.25     .06       0
Bank Sta=229.47,241.1
XS Rating Curve= 0 ,0
Exp/Cntr(USF)=0,0
Exp/Cntr=0.3,0.1

Type RM Length L Ch R = 1 ,8525    ,499.6,498.7,496.8
XS GIS Cut Line= 6
1580295.17613331402470.1978981681580153.80929005402584.617616835
1580021.75804496402700.0058375031579940.68996564 402725.12553792
1579841.92802405402764.4309054941579741.66444504402812.970506582
#Sta/Elev= 30
       0  874.54    19.4  870.26    50.2  869.95    80.1  866.83   105.6  862.16
   137.3  853.54   156.3   844.1   162.7  839.26   168.8  832.21   173.8  824.82
   185.9  810.31   194.5  798.36     200  792.99     205   790.6  216.74790.5567
   225.3  790.29  229.67 790.572   246.8  797.26   262.5  798.97   310.6  800.56
   363.2  800.12   387.8  800.72   442.7  798.27   515.9  799.18   567.8  804.06
   603.8  804.13   609.7  805.01   630.4  810.54   657.1  811.21   659.8  812.29
#Mann= 6 ,-1,0
       0      .1       0  216.74    .045       0  229.67      .1       0
   327.1     .06       0  558.42      .1       0  648.42     .06       0
Bank Sta=216.74,229.67
XS Rating Curve= 0 ,0
Exp/Cntr(USF)=0,0
Exp/Cntr=0.3,0.1

Type RM Length L Ch R = 1 ,8026    ,378.6,378.7,378.2
XS GIS Cut Line= 6
1579953.96036708402039.6568486691579893.85353193402111.852570429
1579741.51525392402325.5962374211579696.85326976402385.930106252
1579634.36979893402449.1012397561579561.71410434402511.678870499
#Sta/Elev= 30
       0  910.39     6.4  908.69    32.4  898.05      48     890    58.7  887.73
    84.4   884.6   129.3  871.29     154  862.53   188.5  847.15   213.2  830.53
   221.7  821.68   227.5  817.01   267.6  792.48   273.4  790.37   302.1  786.17
   307.8  785.84  312.62786.1703   345.2  792.68   399.9  794.93   419.3  797.86
   449.6  797.13   472.4   793.2   487.6  795.23   510.2   796.5   525.6   800.3
   547.1  809.71   569.8  811.34   580.8  814.87   598.1  818.67   616.2  825.64
#Mann= 5 ,-1,0
       0      .1       0  296.41     .06       0   302.1    .045       0
  312.62     .06       0  491.49      .1       0
Bank Sta=302.1,312.62
XS Rating Curve= 0 ,0
Exp/Cntr(USF)=0,0
Exp/Cntr=0.3,0.1

Type RM Length L Ch R = 1 ,7647    ,196.1,195.8,195.4
BEGIN DESCRIPTION:
Structure XS 4
END DESCRIPTION:
XS GIS Cut Line= 3
 1579635.5170856401912.8273895381579492.13098751402033.643453673
1579342.10664413402264.654389491
#Sta/Elev= 30
       0  852.87    18.2  841.54    46.3   825.3    72.4  815.97    92.7  810.33
    98.9  807.44   119.5   794.7   124.3  792.49   132.8  789.77   140.4   788.4
   148.5  788.12   205.3  787.58   219.6  788.07   231.6  787.54   238.8  787.05
   247.4  783.34     253  782.81   257.7  783.38   270.6   787.1   282.1  792.18
   295.9  794.34   325.5  795.68   342.9  795.71     377  793.41   389.1  800.99
   405.6  807.43   444.1  818.16   448.5  820.76     458  828.84     463  832.04
#Mann= 4 ,-1,0
       0      .1       0   247.4    .045       0   257.7     .06       0
   427.5      .1       0
Bank Sta=247.4,257.7
XS Rating Curve= 0 ,0
Exp/Cntr(USF)=0,0
Exp/Cntr=0.3,0.1

Type RM Length L Ch R = 1 ,7452    ,50.7,50.9,50.7
BEGIN DESCRIPTION:
Structure XS 3
END DESCRIPTION:
XS GIS Cut Line= 3
1579485.49274222 401807.943114081579291.65597999 401993.81398198
 1579160.2187234402223.497268741
#Sta/Elev= 30
       0  837.02    12.4  828.79    18.4   827.4    29.7  821.97    58.7  813.16
    77.8  799.83   103.2  789.83   125.9  789.36   148.5  791.93   176.8  791.95
   216.4  787.84   237.8  786.86   268.6  787.38   284.9  786.38   296.6  785.03
  303.38782.2552   308.3  781.54   313.2  782.25   325.9  785.27   334.7  792.38
   340.8  794.32   372.3  794.19   391.5  791.88   396.1  793.27   409.9  805.65
   413.8  808.35   443.2  823.58   460.6  836.67   511.3   862.1   533.2  869.73
#Mann= 7 ,-1,0
       0      .1       0     180     .05       0     250     .07       0
  303.38    .045       0   313.2     .07       0  328.55     .06       0
  368.55      .1       0
Bank Sta=303.38,313.2
XS Rating Curve= 0 ,0
Exp/Cntr(USF)=0,0
Exp/Cntr=0.3,0.1

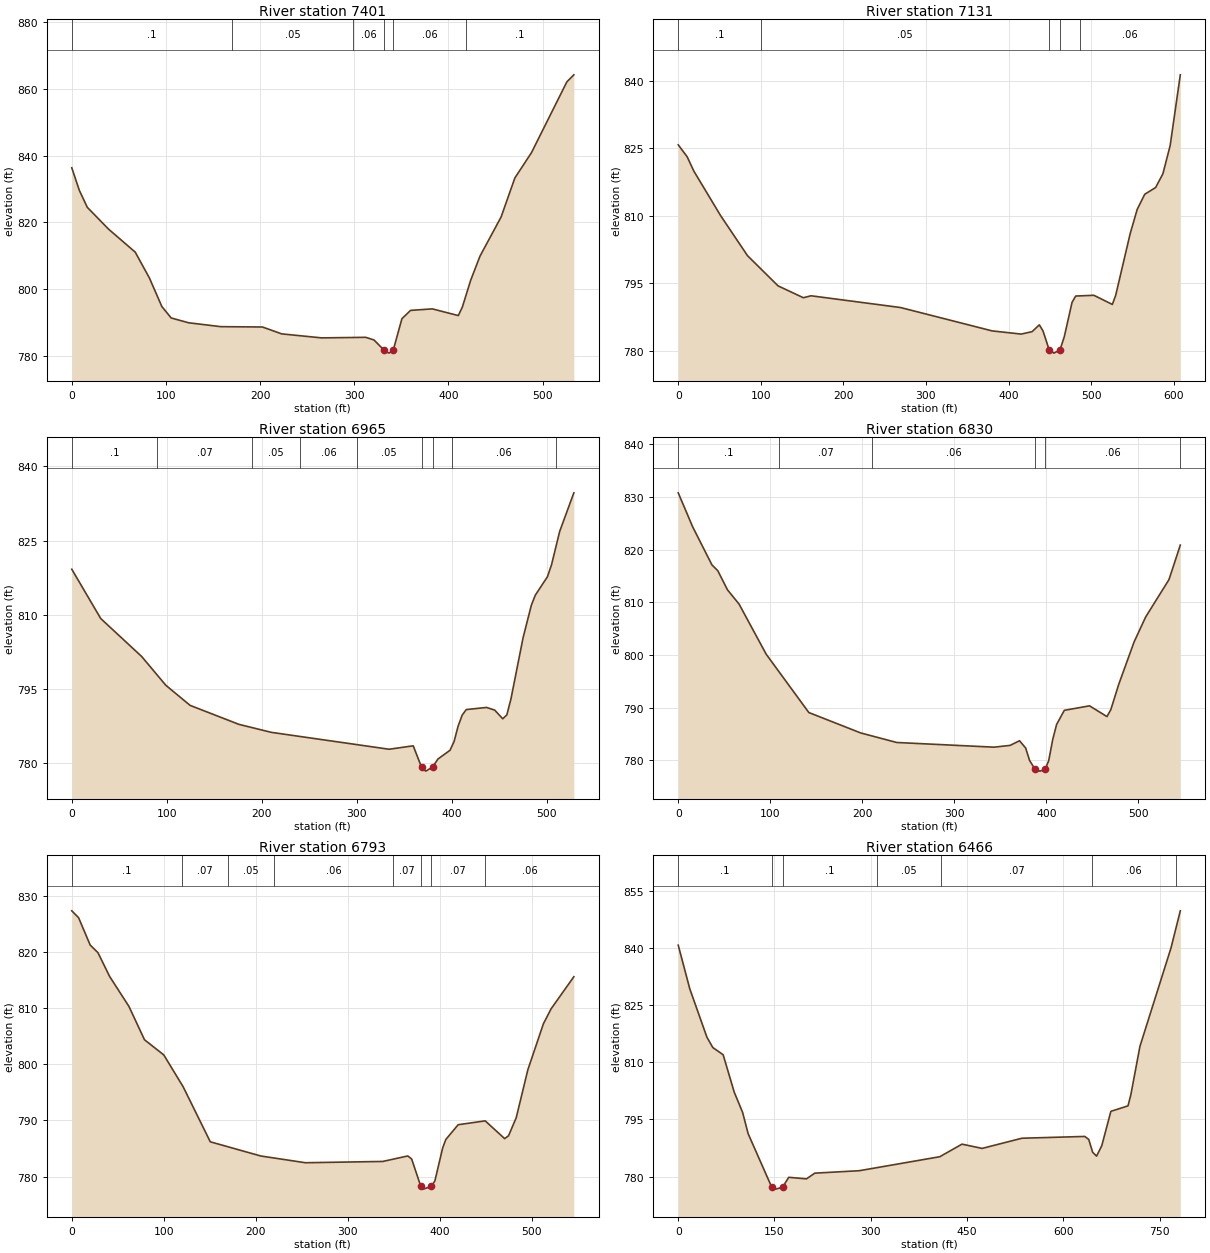
Type RM Length L Ch R = 1 ,7401    ,270,269.7,269.2
BEGIN DESCRIPTION:
Structure XS 2
END DESCRIPTION:
XS GIS Cut Line= 3
1579450.31004223401771.4327650291579256.47327999401957.303632928
 1579125.0360234 402186.98691969
#Sta/Elev= 30
       0  836.35       8  829.61    16.5  824.51    39.1  817.98    67.4   811.1
    82.5  803.34    95.7  794.81   105.6   791.4     124  789.97   158.2   788.8
   202.5   788.7     223  786.64   265.4  785.44   312.2  785.61     321  784.81
  331.64781.7639   336.8  780.88   341.4  781.76   350.6  791.17   359.8  793.67
   382.9  794.12   410.5  792.12   414.8  794.67   423.6  802.65   433.6  809.95
   455.9  821.59   470.6  833.32   488.1  840.82   525.8  862.06   533.2  864.16
#Mann= 6 ,-1,0
       0      .1       0     170     .05       0  298.55     .06       0
  331.64    .045       0   341.4     .06       0  418.55      .1       0
Bank Sta=331.64,341.4
XS Rating Curve= 0 ,0
Exp/Cntr(USF)=0,0
Exp/Cntr=0.3,0.1

Type RM Length L Ch R = 1 ,7131    ,166.7,166.3,165.8
BEGIN DESCRIPTION:
Structure XS 1
END DESCRIPTION:
XS GIS Cut Line= 6
1579098.69148726401497.8916502381579118.67292757 401610.99718904
1579093.72131394 401667.608080051579020.87205019401826.724559715
1578953.22586002401974.4749203831578914.20034752402059.716219729
#Sta/Elev= 30
       0  825.74    10.8   823.1    18.9  819.91    51.4     810    83.9  801.12
   120.9  794.41   151.5  791.78   160.9  792.21   269.2   789.6   380.1  784.41
   415.3   783.7   428.5  784.24   437.3  785.75   441.7  784.41   449.1780.2654
   454.9  779.47   462.3  780.19   467.5  783.12   476.9  790.75   481.3  792.15
   503.3  792.32   525.7  790.29   529.7  792.28   547.3  806.02   555.8  811.41
   564.9  814.76   578.1  816.26   586.9  819.31   595.7  825.57     608   841.3
#Mann= 5 ,-1,0
       0      .1       0     100     .05       0   449.1    .045       0
   462.3     .05       0  486.72     .06       0
Bank Sta=449.1,462.3
XS Rating Curve= 0 ,0
Exp/Cntr(USF)=0,0
Exp/Cntr=0.3,0.1

Type RM Length L Ch R = 1 ,6965    ,135,135,134.4
BEGIN DESCRIPTION:
Structure XS 4
END DESCRIPTION:
XS GIS Cut Line= 2
1578954.33114241401511.9756322641578768.50275928402006.550131115
#Sta/Elev= 30
       0   819.2    30.5  809.24    73.6  801.57    98.9  795.78   124.5  791.71
   175.8  787.88     210  786.26   333.9  782.85   359.3  783.54   368.1   779.2
   372.4  778.43   379.8779.2624   385.2  780.86     398  782.64   402.3  784.42
   406.5   787.5   410.8  789.74   415.1  790.86   436.4  791.29     445  790.76
   453.5     789   457.8  789.78   462.1  792.99   474.9  805.38   483.6  811.95
   487.7  813.95   500.5  817.68   504.8  820.09   513.4  826.84   528.3  834.63
#Mann= 9 ,-1,0
       0      .1       0      90     .07       0     190     .05       0
     240     .06       0     300     .05       0   368.1    .045       0
   379.8     .05       0     400     .06       0     510      .1       0
Bank Sta=368.1,379.8
XS Rating Curve= 0 ,0
Exp/Cntr(USF)=0,0
Exp/Cntr=0.3,0.1

Type RM Length L Ch R = 1 ,6830    ,36.6,36.4,36.5
BEGIN DESCRIPTION:
Structure XS 3
END DESCRIPTION:
XS GIS Cut Line= 5
1578859.48123852401489.7149405351578789.79559484401702.643296205
1578744.30635522401752.9718166351578708.49567722401797.493200094
1578647.52073901401984.289439386
#Sta/Elev= 30
       0  830.78    15.6  824.35    36.6   817.1      43  815.98    53.5  812.36
    66.1  809.65    95.6  800.12   141.9  789.05   198.3  785.17   237.4  783.36
   343.2  782.47   360.6  782.81   370.8  783.69   377.5  782.31   381.7  779.96
  387.78778.2415     393  777.92   398.5  778.23   402.5  779.89   406.9  783.94
   411.1  786.78   419.5  789.47   446.9  790.32   465.8  788.28     470  789.59
   478.6   794.4   495.3  802.46   507.9  807.21   533.2   814.3   545.5  820.85
#Mann= 6 ,-1,0
       0      .1       0     110     .07       0     210     .06       0
  387.78    .045       0   398.5     .06       0  545.51      .1       0
Bank Sta=387.78,398.5
XS Rating Curve= 0 ,0
Exp/Cntr(USF)=0,0
Exp/Cntr=0.3,0.1

Type RM Length L Ch R = 1 ,6793    ,326.4,327.4,322.2
BEGIN DESCRIPTION:
Structure XS 2
END DESCRIPTION:
XS GIS Cut Line= 5
 1578824.1544886401481.4881631571578754.46884492401694.416518826
 1578708.9796053401744.7450392571578673.16892731401789.266422716
1578612.19398909401976.062662007
#Sta/Elev= 30
       0  827.33     7.4  826.11      20  821.24    28.5  819.87    41.1  815.65
    62.1  810.31      79  804.37     100  801.66   121.1  795.97   150.5  786.19
   205.4  783.66   253.9  782.46   337.9  782.69   365.1  783.67   369.3  783.12
  379.22778.2587   381.9  777.76   390.5  778.24   394.5  779.21     403  785.11
   406.4   786.6   419.8  789.23   449.2  789.92   470.3  786.76   474.5  787.25
   482.9  790.48   495.5     799   512.4   807.2   520.8  809.88   545.5  815.59
#Mann= 8 ,-1,0
       0      .1       0     120     .07       0     170     .05       0
     220     .06       0  349.02     .07       0  379.22    .045       0
   390.5     .07       0  449.02     .06       0
Bank Sta=379.22,390.5
XS Rating Curve= 0 ,0
Exp/Cntr(USF)=0,0
Exp/Cntr=0.3,0.1

Type RM Length L Ch R = 1 ,6466    ,393.2,393.1,391.7
BEGIN DESCRIPTION:
Structure XS 1
END DESCRIPTION:
XS GIS Cut Line= 3
1578593.90264255401407.8781984111578393.28011847401893.207686815
1578561.44899895402087.929548424
#Sta/Elev= 30
       0   840.7      18  829.27    44.7  816.57    53.9  813.86      70  811.97
    87.3  802.14   100.3  796.86   108.9  791.28   145.8   777.2   151.9  776.72
  162.51777.2047   172.2  779.82   199.8  779.41   212.8  780.91   282.1  781.55
   407.6  785.22   442.2  788.52   473.5   787.4   535.6  790.07   633.5  790.54
   639.7  789.76   645.8  786.39   651.9  785.38     660  788.11   674.2  797.12
   700.9  798.56   705.4  801.54   719.5  814.18   767.8  839.93   782.4  849.72
#Mann= 7 ,-1,0
       0      .1       0   145.8    .045       0  162.51      .1       0
     310     .05       0     410     .07       0  645.16     .06       0
  775.16      .1       0
Bank Sta=145.8,162.51
XS Rating Curve= 0 ,0
Exp/Cntr(USF)=0,0
Exp/Cntr=0.3,0.1

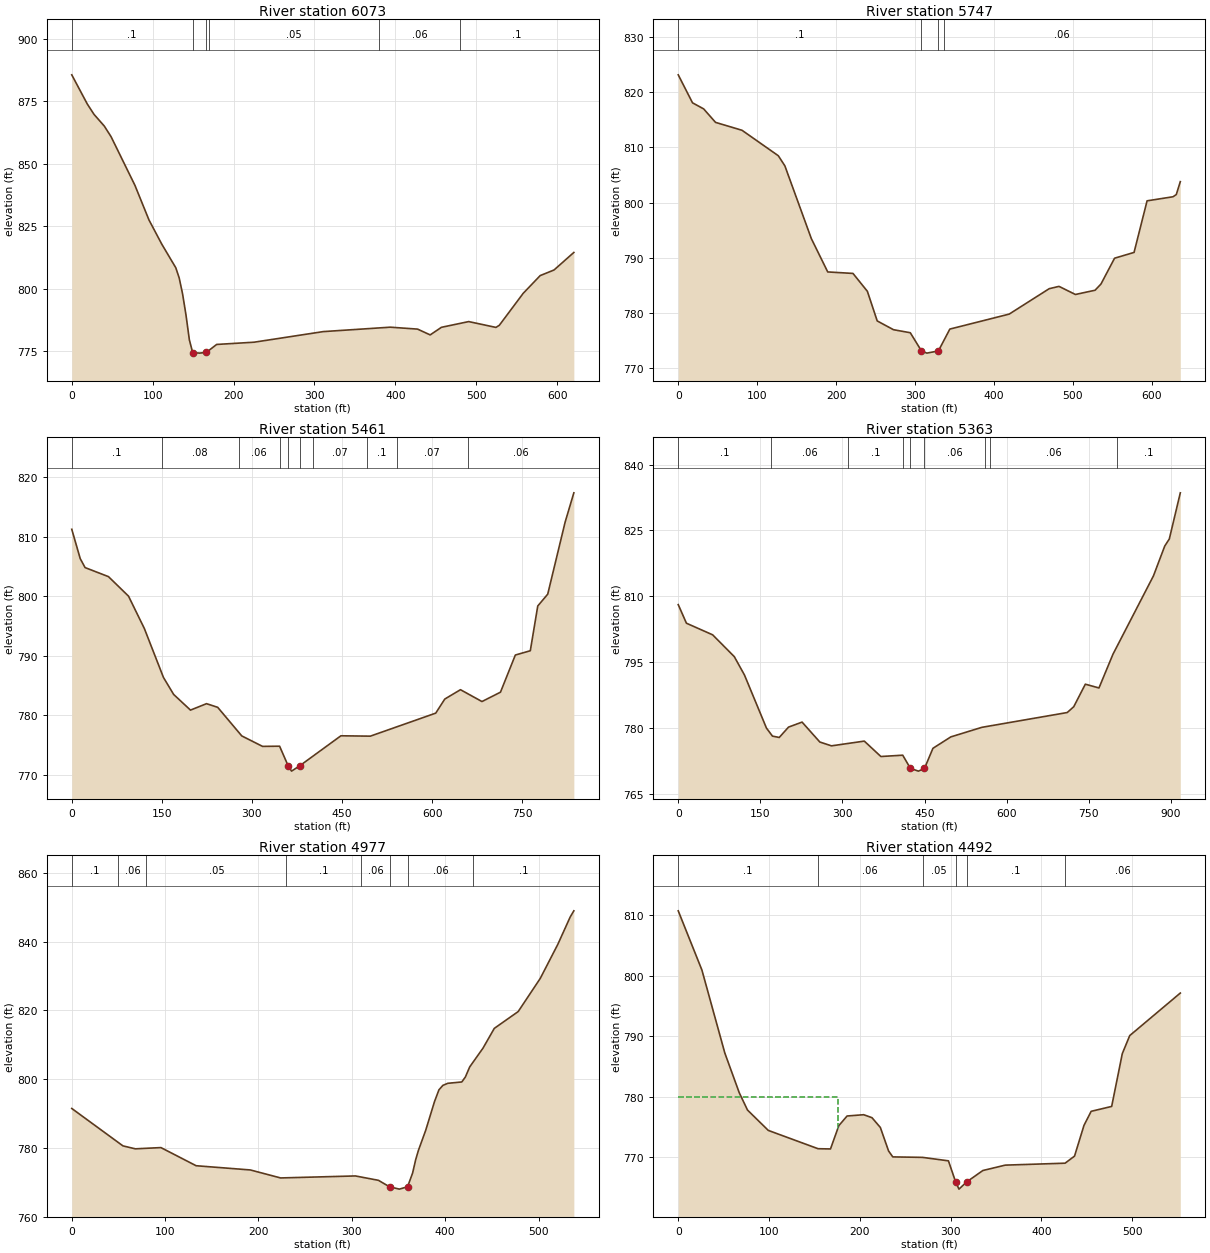
Type RM Length L Ch R = 1 ,6073    ,323.6,325.4,324.6
XS GIS Cut Line= 2
1578230.39073169401234.364783907 1578036.6949695401824.073397093
#Sta/Elev= 30
       0  885.54    19.1  873.92    27.5  869.72    40.2  865.04    48.6  860.78
    78.1  841.32    95.4  827.51   111.3  817.78   128.6  808.35   132.8  804.28
     137  797.88   141.2  789.47   145.4  779.47  149.48 774.426   158.1  774.19
   166.5   774.5   179.1  777.66   225.4  778.56   310.9   782.8   393.8  784.57
   427.5   783.8   443.1  781.48     457  784.52   490.7  786.81   524.4  784.48
   528.6  785.34   558.1  798.12   579.1  805.21   596.2  807.45   620.7  814.47
#Mann= 6 ,-1,0
       0      .1       0  149.48    .045       0   166.5      .1       0
     170     .05       0     380     .06       0     480      .1       0
Bank Sta=149.48,166.5
XS Rating Curve= 0 ,0
Exp/Cntr(USF)=0,0
Exp/Cntr=0.3,0.1

Type RM Length L Ch R = 1 ,5747    ,295.4,286,279.5
BEGIN DESCRIPTION:
Structure XS 4
END DESCRIPTION:
XS GIS Cut Line= 6
1577954.95226125401071.2292863221577880.63712117401316.466984832
1577851.46165458401412.1163998341577825.18841317401491.186451668
1577799.82921192401583.7925656681577776.30432458401681.542698243
#Sta/Elev= 30
       0  823.17    18.1  818.09    32.2  816.99    47.3  814.54    80.8  813.11
   126.8  808.49   135.1  806.66   168.6  793.47   189.4  787.41   221.4  787.14
   239.6   783.9   252.1  778.52   272.7  776.93     294  776.38     308  773.12
   314.9  772.68   329.6773.0773   344.1  777.04   419.3  779.76     470  784.37
   482.4  784.79   503.2  783.32   528.1  784.09   535.6  785.22   552.8   789.9
   577.5  790.95     594  800.31   626.9  801.05     631  801.45   636.1  803.79
#Mann= 4 ,-1,0
       0      .1       0     308    .045       0   329.6      .1       0
  336.25     .06       0
Bank Sta=308,329.6
XS Rating Curve= 0 ,0
Exp/Cntr(USF)=0,0
Exp/Cntr=0.3,0.1

Type RM Length L Ch R = 1 ,5461    ,99.4,98.1,95.8
BEGIN DESCRIPTION:
Structure XS 3
END DESCRIPTION:
XS GIS Cut Line= 6
1577644.15835363400988.6030260971577506.74667629 401130.79424004
 1577581.2269599401235.8282776761577628.38836726401293.769435291
1577768.42630531401434.2948143391577706.29232947401662.517687139
#Sta/Elev= 30
       0  811.28    14.1  806.34    22.2  804.84    61.1  803.32    94.5  800.04
   120.9  794.59   152.7  786.37   169.7  783.51   197.7  780.88   224.4  781.96
     243  781.35   283.1  776.54   317.7  774.78   346.1  774.81   360.3  771.52
     366  770.62  379.58 771.515   448.2  776.56   497.2   776.5   606.1  780.37
   621.2  782.74   647.3  784.31   683.1  782.32   713.9  783.89   738.7  790.14
   763.6  790.86     776  798.38   792.6  800.37   821.6  812.49   836.1  817.41
#Mann= 10 ,-1,0
       0      .1       0     150     .08       0  277.74     .06       0
   346.5      .1       0   360.3    .045       0  379.58      .1       0
  401.21     .07       0  491.21      .1       0  541.21     .07       0
   659.6     .06       0
Bank Sta=360.3,379.58
XS Rating Curve= 0 ,0
Exp/Cntr(USF)=0,0
Exp/Cntr=0.3,0.1

Type RM Length L Ch R = 1 ,5363    ,366.3,386.6,402
BEGIN DESCRIPTION:
Structure XS 2
END DESCRIPTION:
XS GIS Cut Line= 4
1577601.73996628400969.4848796841577412.94827046 401176.19983777
1577674.62789948401479.7004120691577612.49392364401707.923284868
#Sta/Elev= 30
       0  808.08      15  803.84    62.8   801.2   102.4  796.23     121  792.04
   161.2  779.94   172.1  778.12   184.5  777.81   201.5  780.17   226.2  781.31
   258.7  776.77     280   775.9   339.9  776.98   370.2  773.47   410.1  773.77
   424.2  770.76   438.8  770.14  449.86 770.751   465.3  775.34     498  777.94
   554.7  780.12   710.6  783.49   722.5  784.81   743.7  789.95   768.6  789.09
   794.2  796.78   868.1  814.62   888.8  821.44   897.1  823.03   917.2  833.55
#Mann= 9 ,-1,0
       0      .1       0     170     .06       0  309.95      .1       0
  409.95     .06       0   424.2    .045       0  449.86     .06       0
  559.95     .07       0  569.95     .06       0  800.69      .1       0
Bank Sta=424.2,449.86
XS Rating Curve= 0 ,0
Exp/Cntr(USF)=0,0
Exp/Cntr=0.3,0.1

Type RM Length L Ch R = 1 ,4977    ,482.4,485.1,481.6
BEGIN DESCRIPTION:
Structure XS 1
END DESCRIPTION:
XS GIS Cut Line= 2
1577457.95086576400974.8211430931577001.52864276401259.241887963
#Sta/Elev= 30
       0   791.5    54.8  780.63    68.1  779.77    95.5  780.13   133.2  774.86
   191.3  773.63   223.7  771.31   303.8  771.89   328.5  770.62  340.37768.7329
   350.9  768.06   359.7  768.75   365.1  772.74   368.4  776.64   371.3   779.3
   379.2  785.22   388.6  793.54   393.3  796.91   397.5  798.21   402.8  798.81
   417.8   799.2   421.6  800.64   426.3  803.59   440.5  809.03   452.6  814.77
   478.2  819.66   501.8  829.28   520.6  839.17   533.9  847.14   537.8  848.93
#Mann= 8 ,-1,0
       0      .1       0      50     .06       0      80     .05       0
     230      .1       0     310     .06       0  340.37    .045       0
   359.7     .06       0     430      .1       0
Bank Sta=340.37,359.7
XS Rating Curve= 0 ,0
Exp/Cntr(USF)=0,0
Exp/Cntr=0.3,0.1

Type RM Length L Ch R = 1 ,4492    ,478.1,479.4,479.9
BEGIN DESCRIPTION:
Low water crossing
END DESCRIPTION:
XS GIS Cut Line= 6
1577322.91466905400549.6355955041577074.98628259400686.673988058
1577043.78222681400716.2505209851577037.16175184400729.745255923
1577034.83097485400754.2038292981576915.27084155400898.208039168
#Sta/Elev= 30
       0  810.68    26.1   800.9    51.3  787.22    67.2  780.66    76.3   777.8
    99.2  774.44     154  771.42   167.7  771.38   176.9  775.23     186  776.82
   204.3  777.03   213.4  776.54   222.6  774.93   231.7  771.04   236.3  770.07
   269.1  769.99   297.6  769.42  305.44 765.992   309.2  764.75   317.8  765.95
   335.5  767.82   360.2  768.71   426.1  769.03   436.5   770.2   446.9  775.27
   454.8  777.59   477.4   778.4   489.1  787.11   497.3  790.09     553  797.11
#Mann= 6 ,-1,0
       0      .1       0     154     .06       0   269.1     .05       0
  305.44    .045       0   317.8      .1       0   426.1     .06       0
#XS Ineff= 2 , 0
          175.56  779.97
Permanent Ineff=
       F       F
Bank Sta=305.44,317.8
XS Rating Curve= 0 ,0
Exp/Cntr(USF)=0,0
Exp/Cntr=0.3,0.1

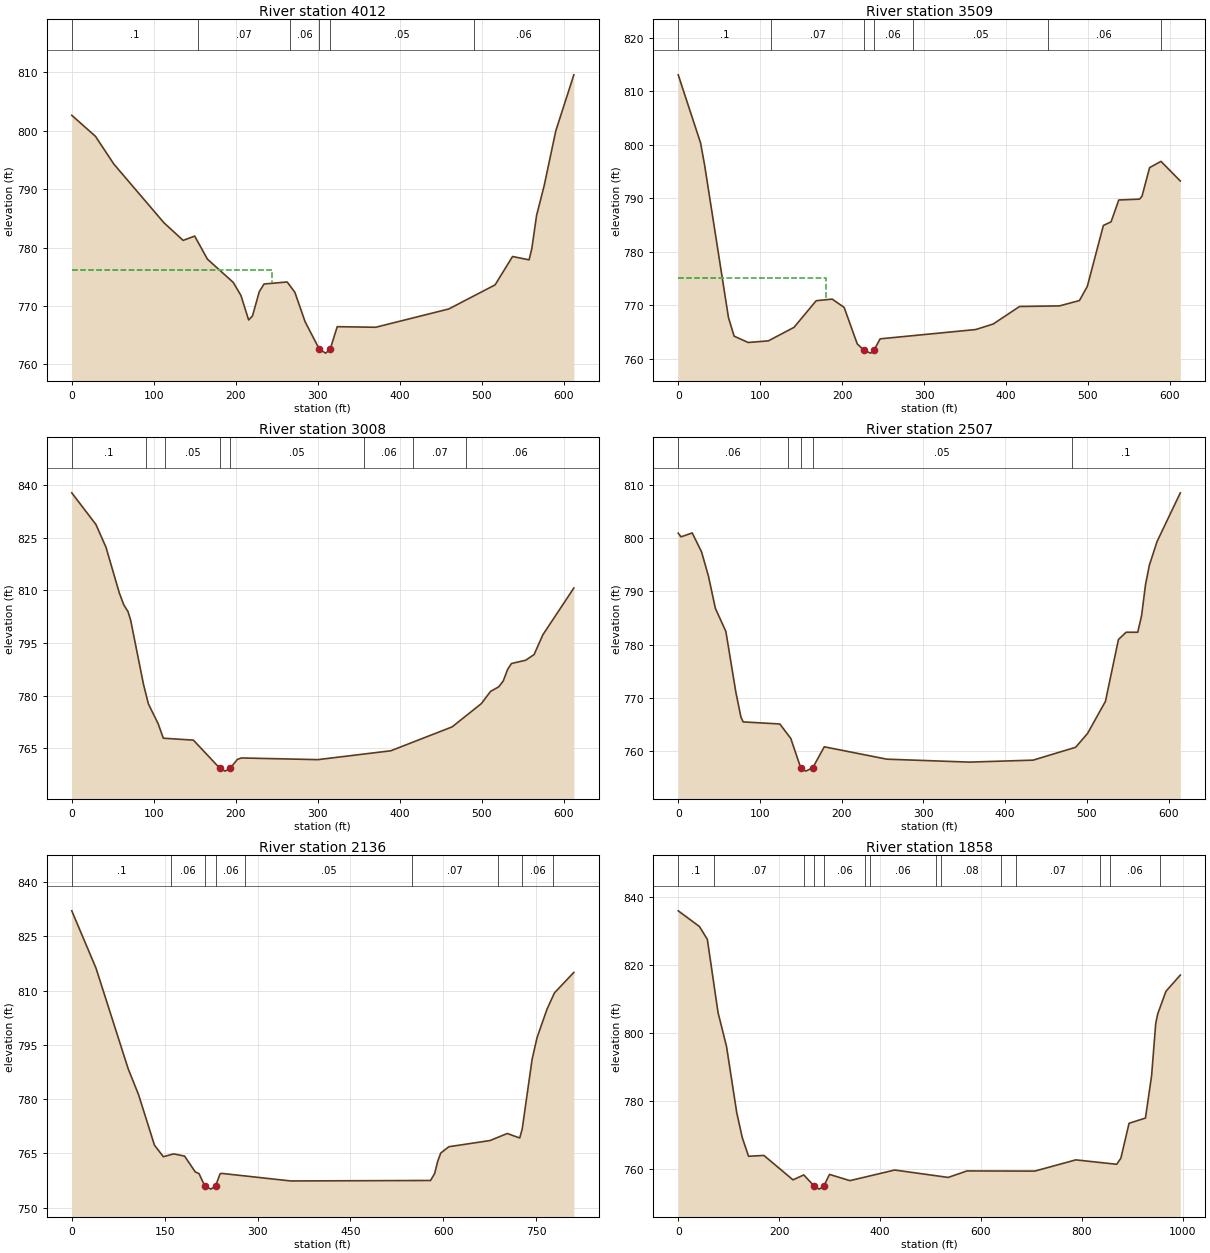
Type RM Length L Ch R = 1 ,4012    ,502.6,503.2,501.8
XS GIS Cut Line= 6
  1577127.812148400148.4509854171576973.52210225400243.562015668
1576824.55258392400335.3938530091576760.70789534400374.750073507
1576686.22313617400420.6656640921576604.60682958400466.969705343
#Sta/Elev= 30
       0  802.67    28.9  799.07    51.3  794.32   112.4  784.27   135.9  781.24
     150  781.98   165.5  778.03     197  774.05   206.4  771.81   215.8  767.61
   220.5   768.3   228.8  772.46   234.6  773.77   262.8  774.12   272.2  772.36
   284.7  767.31   302.2  762.57   309.8  761.93   315.3762.5981   323.9  766.46
   370.9  766.36   460.1   769.5   516.5  773.62   537.8  778.48     558  777.91
   561.3  779.81   567.1   785.5   576.4  790.62   590.6  800.01   612.6   809.6
#Mann= 6 ,-1,0
       0      .1       0  153.75     .07       0  266.25     .06       0
   302.2    .045       0   315.3     .05       0  491.25     .06       0
#XS Ineff= 2 , 0
          244.57  776.12
Permanent Ineff=
       F       F
Bank Sta=302.2,315.3
XS Rating Curve= 0 ,0
Exp/Cntr(USF)=0,0
Exp/Cntr=0.3,0.1

Type RM Length L Ch R = 1 ,3509    ,501.1,501,499.3
XS GIS Cut Line= 6
1576794.47877135399756.0111904181576583.91390377399902.046987582
1576501.74182401399959.0360468371576440.11333834400001.778415416
1576368.21354776 400051.645441671576288.28949501400101.186353076
#Sta/Elev= 30
       0  813.04    27.2  800.34    32.1  796.25    61.3  767.67    68.2  764.18
    85.4     763     110   763.3   141.3  765.83   168.4  770.81   187.9  771.11
   202.5  769.56   218.5  762.74   226.8  761.52   234.9  761.01  238.75761.5158
   246.4  763.68   363.1  765.42   384.4  766.45   416.6  769.73   465.3  769.84
   489.7  770.84   499.3  773.49   518.9  784.88   528.3  785.56   537.7  789.64
     563   789.8     566  790.32   575.3  795.69   589.2  796.86   612.8  793.19
#Mann= 7 ,-1,0
       0      .1       0  113.75     .07       0   226.8    .045       0
  238.75     .06       0  286.25     .05       0  451.25     .06       0
  588.75      .1       0
#XS Ineff= 2 , 0
          180.16     775
Permanent Ineff=
       F       F
Bank Sta=226.8,238.75
XS Rating Curve= 0 ,0
Exp/Cntr(USF)=0,0
Exp/Cntr=0.3,0.1

Type RM Length L Ch R = 1 ,3008    ,501,500.8,500.7
XS GIS Cut Line= 6
1576471.13982802399345.9634848381576401.48314319399408.708110004
1576336.47014986399467.2686884251576280.74617995399517.463141843
1576150.71691244399634.5879075971576016.04428152399755.895735845
#Sta/Elev= 30
       0  837.88    29.5  828.83    41.8  822.31    57.9  809.37    63.4  805.93
    68.7  803.92    71.9  801.45    87.5   783.2    93.5   777.6   105.4  771.94
   111.7  767.81   148.4  767.26  180.87759.1655   187.1  758.41  193.15759.2279
   202.2  761.79     207  762.17   300.2  761.69   389.2  764.22     464  771.04
   499.6  777.68   510.9  781.18   520.9  782.49   526.3  784.12   531.7  787.44
   536.4  789.14   553.7  790.08     564  791.69   574.7  797.34   612.5   810.7
#Mann= 8 ,-1,0
       0      .1       0      90     .06       0  113.75     .05       0
  180.87    .045       0  193.15     .05       0  356.25     .06       0
  416.25     .07       0  481.25     .06       0
Bank Sta=180.87,193.15
XS Rating Curve= 0 ,0
Exp/Cntr(USF)=0,0
Exp/Cntr=0.3,0.1

Type RM Length L Ch R = 1 ,2507    ,370.5,371.3,371.5
XS GIS Cut Line= 6
1576186.05671678398946.3373294391576115.21105794399007.737469099
1575916.84236019399179.6564166021575857.97371153399226.246874608
1575784.29669353399274.8366724321575704.03044986399325.297529511
#Sta/Elev= 30
       0  800.89     3.4  800.21    17.1  800.94    28.5   797.4      37  792.83
    45.5  786.78    58.3  782.47    70.5  771.09    76.7  766.43    79.5  765.51
   124.3  765.12   137.7  762.42   149.9  756.89     156  756.28   164.6   756.9
   178.7  760.84   255.3  758.52   356.3  757.97   434.3  758.34   486.3  760.75
   500.9  763.35   522.8  769.37   538.7  780.96   548.1  782.32   562.3  782.32
     567  785.42   571.8  791.22   576.5  794.88   585.9  799.31   614.4  808.46
#Mann= 5 ,-1,0
       0     .06       0  133.75     .05       0   149.9    .045       0
   164.6     .05       0  481.32      .1       0
Bank Sta=149.9,164.6
XS Rating Curve= 0 ,0
Exp/Cntr(USF)=0,0
Exp/Cntr=0.3,0.1

Type RM Length L Ch R = 1 ,2136    ,278.4,277.9,273.7
XS GIS Cut Line= 3
1576041.80760624398611.6727778541575526.41023592398986.838354841
1575520.94665955399159.851606364
#Sta/Elev= 30
       0  832.08    39.1  816.24    91.1  788.38   107.8  781.24   133.5  767.26
   147.9  764.06   164.6  764.84   182.2  764.22   199.4  759.84   205.4   759.4
   214.8  755.95   224.7  755.09  232.27756.0394   239.5  759.35   242.3  759.44
   353.4  757.35   579.2  757.48   585.9  759.42   590.8  762.79   595.8  765.09
   608.8  766.82   675.2  768.53   703.2  770.48   723.2  769.24   727.2  771.68
   743.2  790.99   751.2     797   767.2  804.84   779.3  809.38   810.6  815.05
#Mann= 9 ,-1,0
       0      .1       0     160     .06       0   214.8    .045       0
  232.27     .06       0     280     .05       0     550     .07       0
  687.48      .1       0  727.48     .06       0  777.48     .07       0
Bank Sta=214.8,232.27
XS Rating Curve= 0 ,0
Exp/Cntr(USF)=0,0
Exp/Cntr=0.3,0.1

Type RM Length L Ch R = 1 ,1858    ,85.6,87.2,90.6
XS GIS Cut Line= 3
1575859.68839411398353.0634966291575402.56917167398877.566827563
1575453.56255106399172.599951213
#Sta/Elev= 30
       0  836.02      42  831.41    57.7  827.62    78.9  806.05    95.7  796.07
     116  776.53   126.9  769.22   139.4   763.7   169.8  763.95   227.5  756.75
   248.8  758.21  269.46754.9153   279.4  754.02   288.5   754.9   299.8  758.36
   340.3  756.52   429.1  759.65   535.1  757.47   572.3  759.38   706.6  759.33
   788.1  762.64   869.2  761.34   877.4  763.15   893.6  773.42   926.1  774.96
   938.3  787.46   946.4  802.73   950.4  805.65   966.7   812.3   995.2  817.09
#Mann= 14 ,-1,0
       0      .1       0      70     .07       0     250     .06       0
  269.46    .045       0   288.5     .06       0     370     .07       0
     380     .06       0     510     .05       0     520     .08       0
     640     .05       0     670     .07       0  835.75     .05       0
  855.75     .06       0  955.75     .07       0
Bank Sta=269.46,288.5
XS Rating Curve= 0 ,0
Exp/Cntr(USF)=0,0
Exp/Cntr=0.3,0.1

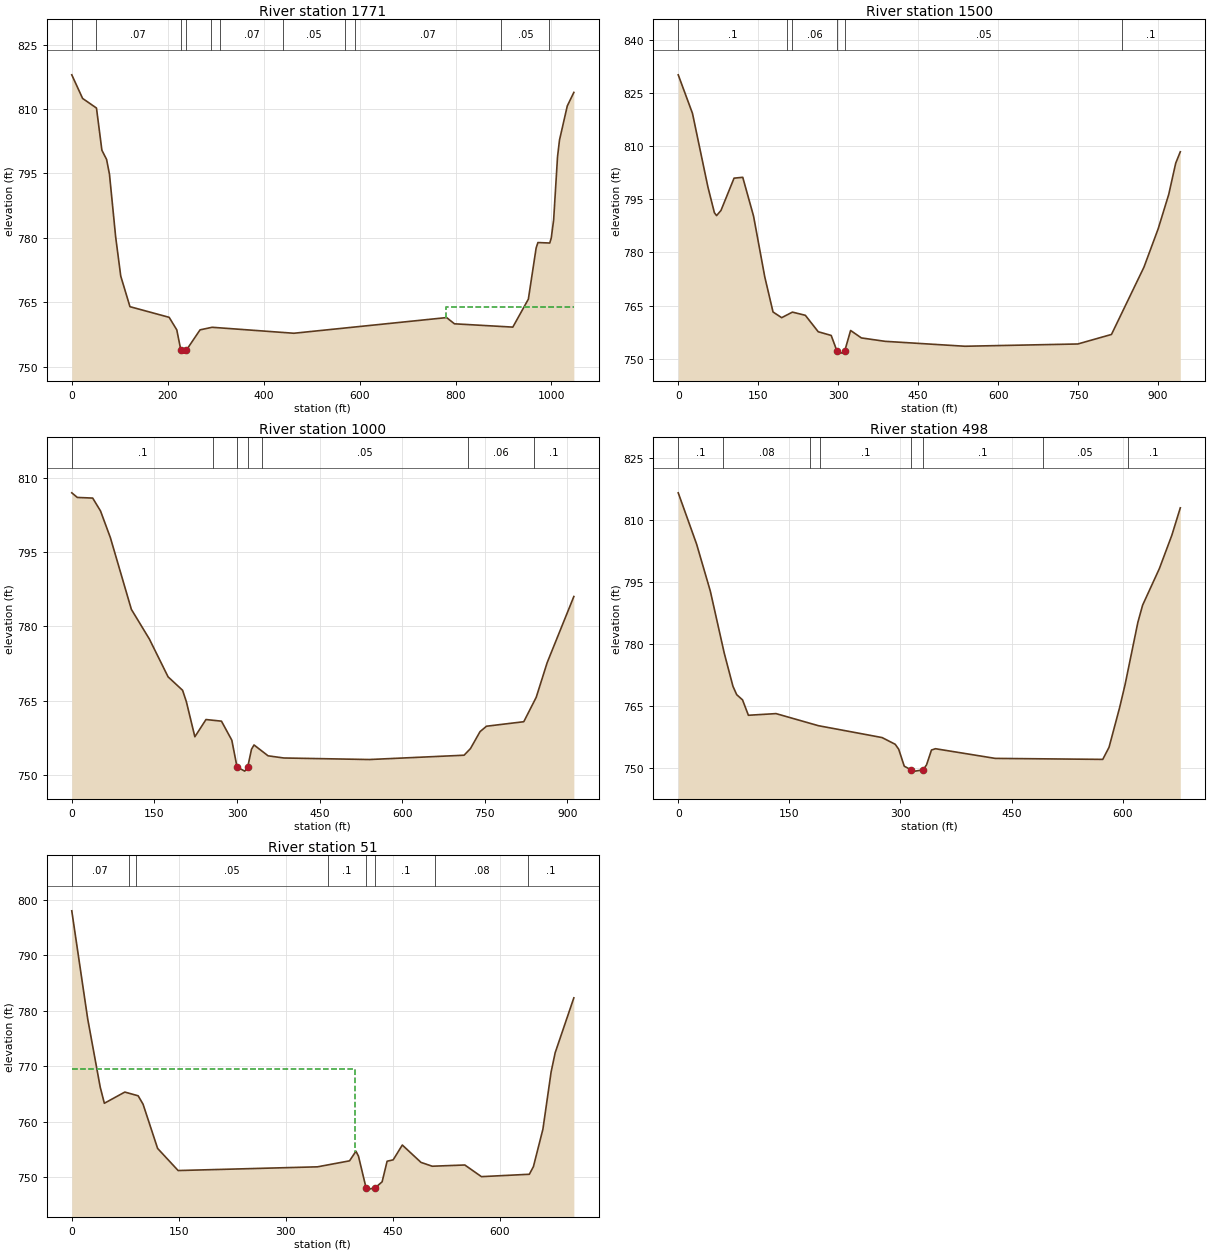
Type RM Length L Ch R = 1 ,1771    ,264.2,270.7,273.6
BEGIN DESCRIPTION:
Structure XS 2
END DESCRIPTION:
XS GIS Cut Line= 3
1575807.78441866398307.5336935971575350.66519621398832.037024531
1575408.94334409399178.063527577
#Sta/Elev= 30
       0  817.95    22.6  812.45    51.5  810.21    62.8  800.39    72.6  798.23
    78.6  794.79    91.5  780.18   102.1  771.07   121.3  763.94     203  761.46
   218.9  758.54   227.3  753.86   230.1  753.12  239.14753.8568   267.4  758.54
   292.5  759.14   462.9  757.75   781.4   761.4   797.7  759.95   919.4  759.18
   951.8   765.7     968  777.61   971.7  778.88   996.4  778.77   999.5  779.93
  1004.5  784.16  1012.6  798.88  1016.7  802.76  1032.9  810.69  1046.6  813.85
#Mann= 11 ,-1,0
       0      .1       0      50     .07       0   227.3    .045       0
  239.14     .07       0     290     .05       0     310     .07       0
     440     .05       0     570     .08       0     590     .07       0
  895.75     .05       0  995.75     .06       0
#XS Ineff= 2 , 0
                          779.87          763.77
Permanent Ineff=
       F       F
Bank Sta=227.3,239.14
XS Rating Curve= 0 ,0
Exp/Cntr(USF)=0,0
Exp/Cntr=0.3,0.1

Type RM Length L Ch R = 1 ,1500    ,503.7,499.6,497.8
BEGIN DESCRIPTION:
Structure XS 1
END DESCRIPTION:
XS GIS Cut Line= 6
1575822.02046825398201.981781259  1575729.484236398224.485017091
1575642.70849092398239.3284913451575568.41598859398249.646712169
 1575020.1188262398331.2091911741574917.67491187398409.729486456
#Sta/Elev= 30
       0  830.08    26.7  819.21    55.5  798.55    67.8  791.19    71.9  790.36
    80.2  791.83   104.7  800.93     121  801.17   141.3  790.21   162.3  773.08
   177.8  763.18     194  761.57   214.2  763.14   238.4  762.24   262.6   757.6
   286.9  756.56  297.51752.2473   307.1  751.57   312.4  752.24   323.3  757.96
   343.5  755.86     388   754.9   537.7  753.51   749.5  754.15   812.6  756.84
   873.5  775.82   900.3   786.7     920  796.35   933.1  805.17   941.7  808.37
#Mann= 6 ,-1,0
       0      .1       0  203.27     .07       0  213.27     .06       0
  297.51    .045       0   312.4     .05       0  832.61      .1       0
Bank Sta=297.51,312.4
XS Rating Curve= 0 ,0
Exp/Cntr(USF)=0,0
Exp/Cntr=0.3,0.1

Type RM Length L Ch R = 1 ,1000    ,499.1,502.3,498.7
XS GIS Cut Line= 6
  1575544.791692397669.0415741651575325.39318067397801.435994416
1575240.22438775397853.8482911741575177.13757168397894.606411755
1575102.08129135397940.3225276771574769.76383034398148.846524179
#Sta/Elev= 30
       0  806.93    10.1     806      38  805.87    52.2  803.27    70.1  797.89
   108.2  783.42   140.9  777.43   174.9   769.8   201.2  767.09   208.1  764.78
   223.5  757.71   243.7  761.19   271.8  760.86   290.6  757.02   300.1   751.6
   314.1  750.78  319.44751.5912   326.3  755.18   330.9  756.06   356.4  753.87
     385  753.43   540.5  753.12   712.3  753.99   723.9  755.33   741.3  758.75
     753  759.84   820.7  760.75   843.3  765.68   863.2  772.68   911.6  786.01
#Mann= 7 ,-1,0
       0      .1       0  256.25     .07       0   300.1    .045       0
  319.44     .07       0  346.25     .05       0  719.24     .06       0
  839.24      .1       0
Bank Sta=300.1,319.44
XS Rating Curve= 0 ,0
Exp/Cntr(USF)=0,0
Exp/Cntr=0.3,0.1

Type RM Length L Ch R = 1 ,498     ,449.4,447.3,442.9
XS GIS Cut Line= 6
1575131.81679617397303.1338414251575030.89606626397465.737846926
 1574979.0585715397527.736738667 1574888.5075715397570.334422499
1574774.33457151397701.1314050111574679.86763543397792.327915888
#Sta/Elev= 30
       0  816.52    24.8  804.11    43.3  792.76    62.2  777.68    73.9  769.71
    78.9  767.71    86.8  766.44    94.7  762.72     132  763.12   189.2   760.2
   275.1  757.33   292.9   755.7   297.6   754.5   305.1   750.4  314.32749.5213
   319.7  749.21   330.5  749.52   335.2  750.74   341.8  754.31   347.2  754.63
   427.9  752.29     573  752.05   581.5  754.98   595.7  764.52   603.2  770.18
   620.4  785.19   626.8  789.34   649.4  798.18   666.3  806.28   677.7  812.89
#Mann= 8 ,-1,0
       0      .1       0      60     .08       0  178.27     .05       0
  191.45      .1       0  314.32    .045       0   330.5      .1       0
  491.76     .05       0  606.43      .1       0
Bank Sta=314.32,330.5
XS Rating Curve= 0 ,0
Exp/Cntr(USF)=0,0
Exp/Cntr=0.3,0.1

Type RM Length L Ch R = 1 ,51      ,,,
XS GIS Cut Line= 2
1574887.90042166397000.7424372611574397.92153904397506.496413187
#Sta/Elev= 30
       0     798    22.3  778.55    39.9  766.21    45.7   763.3    74.4  765.32
    93.1  764.65     100  763.13   120.4  755.16   149.2  751.17   344.6  751.84
   389.6  752.92   398.6  754.65   402.1  753.78   412.7  748.09   417.4  747.82
  425.94748.0912   435.3  749.14   442.3  752.85   450.8   753.1   463.6  755.77
   489.8  752.64   505.6  751.95   551.3  752.17   574.6  750.07   641.8   750.5
   647.5  751.88   660.8  758.62   672.3  768.93     678  772.41   704.2  782.31
#Mann= 8 ,-1,0
       0     .07       0      80     .06       0      90     .05       0
     360      .1       0   412.7    .045       0  425.94      .1       0
     510     .08       0     640      .1       0
#XS Ineff= 2 , 0
           397.8  769.57
Permanent Ineff=
       F       F
Bank Sta=412.7,425.94
XS Rating Curve= 0 ,0
Exp/Cntr(USF)=0,0
Exp/Cntr=0.3,0.1
LCMann Table=0

Chan Stop Cuts=-1
Use User Specified Reach Order=0
Composite Channel Slope=5